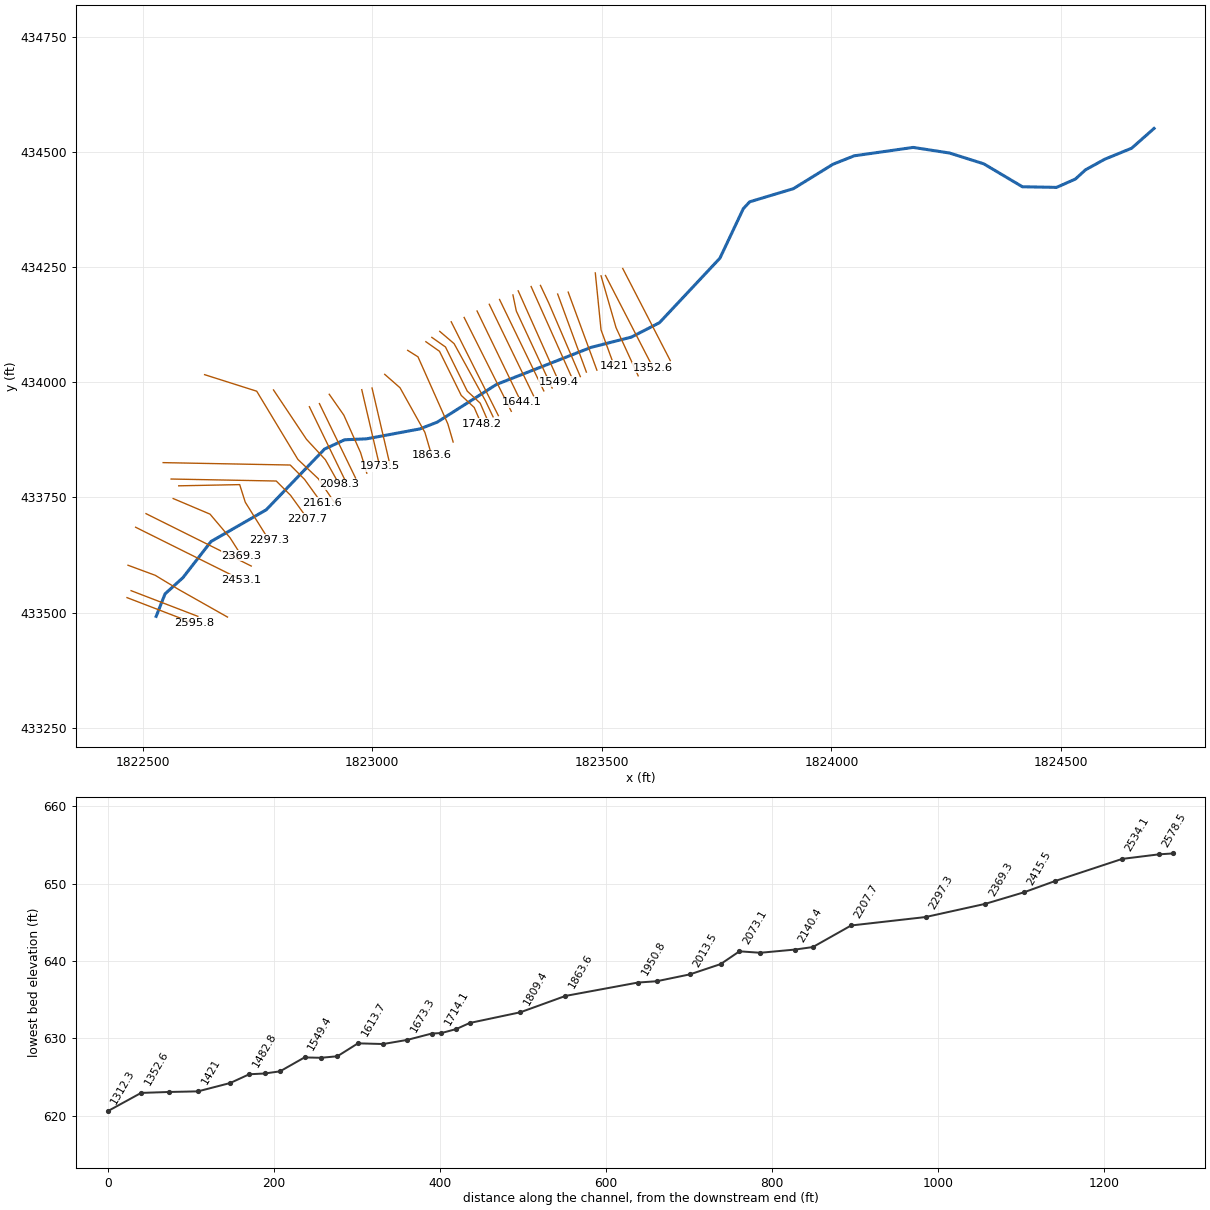
--- LITTLECK.prj (project) ---

Proj Title=LITTLECK
Current Plan=p01
Default Exp/Contr=0,0
English Units
Geom File=g01
Flow File=f01
Plan File=p01
BEGIN DESCRIPTION:
END DESCRIPTION:
DSS Export Rating Curves= 0
DSS Export Rating Curve Sorted= 0
DSS Export Volume Flow Curves= 0
DXF OffsetX= 0
DXF OffsetY= 0
DXF ScaleX= 0
DXF ScaleY= 0

--- LITTLECK.p01 (plan) ---

Plan Title=Floodplain
Program Version=4.00
Geom File=g01
Flow File=f01
K Sum by GR=0
Std Step Tol=0.01
Critical Tol=0.01
Num of Std Step Trials=20
Max Error Tol=0.3
Flow Tol Ratio=0.001
Split Flow NTrial=30
Split Flow Tol=0.02
Split Flow Ratio=0.02
Log Output Level=0
Friction Slope Method=1
Unsteady Friction Slope Method=2
Unsteady Bridges Friction Slope Method=1
Global Log Level=0
CheckData=False
Run HTab=0
Run UNet=0
Run PostProcess=0
UNET Theta=0
UNET Theta Warmup=0
UNET ZTol=0
UNET ZSATol=0
UNET MxIter=0
UNET MaxInSteps=0
UNET DtIC=0
UNET DtMin=0
UNET MaxCRTS=0
UNET WFStab=0
UNET SFStab=0
UNET WFX=0
UNET SFX=0
UNET DSS MLevel=0
UNET DZMax Abort=0
UNET Convert EG Bridges=0
UNET Use Existing IB Tables=0
UNET Froude Limit=0
UNET Froude Power=0
Write IC File=0
Echo Input=False
Echo Output=False
Write Detailed=0

--- LITTLECK.f01 (steady flow) ---

Flow Title=NFF Regression Equation
Program Version=4.10
Number of Profiles= 1
Profile Names=P100yr
River Rch & RM=LITTLECK,Main            ,2595.8
805.5441
River Rch & RM=LITTLECK,Main            ,2098.3
963.7154
River Rch & RM=LITTLECK,Main            ,404.8
990.0602
Boundary for River Rch & Prof#=LITTLECK,Main            , 1
Up Type= 0
Dn Type= 3
Dn Slope=0.014
DSS Import GetInterval= 0
DSS Import GetPeak= 0
DSS Import FillOption= 0

--- LITTLECK.g01 (geometry) ---

Geom Title=USGS 10m DEM
Program Version=4.10

River Reach=LITTLECK        ,Main
Reach XY= 30
     1822529.571      433491.793     1822548.948      433540.609
     1822587.904      433575.821     1822649.015      433654.293
     1822769.154      433723.043     1822896.238      433854.988
     1822939.988      433875.127     1822987.904       433877.21
     1823103.876      433898.738     1823141.376      433913.321
     1823270.543      433995.265     1823476.793      434075.821
     1823564.293      434098.043     1823625.404      434129.293
     1823757.062      434269.354     1823808.104      434377.009
     1823821.993      434391.765     1823917.071      434420.265
     1824003.417      434473.363     1824049.423      434491.592
     1824177.896      434509.821     1824256.889      434497.668
     1824331.542      434474.231     1824415.682      434424.432
     1824489.988      434423.043      1824530.96      434441.099
     1824553.182      434461.238     1824594.849      434484.154
      1824653.59      434508.085     1824702.353      434551.067

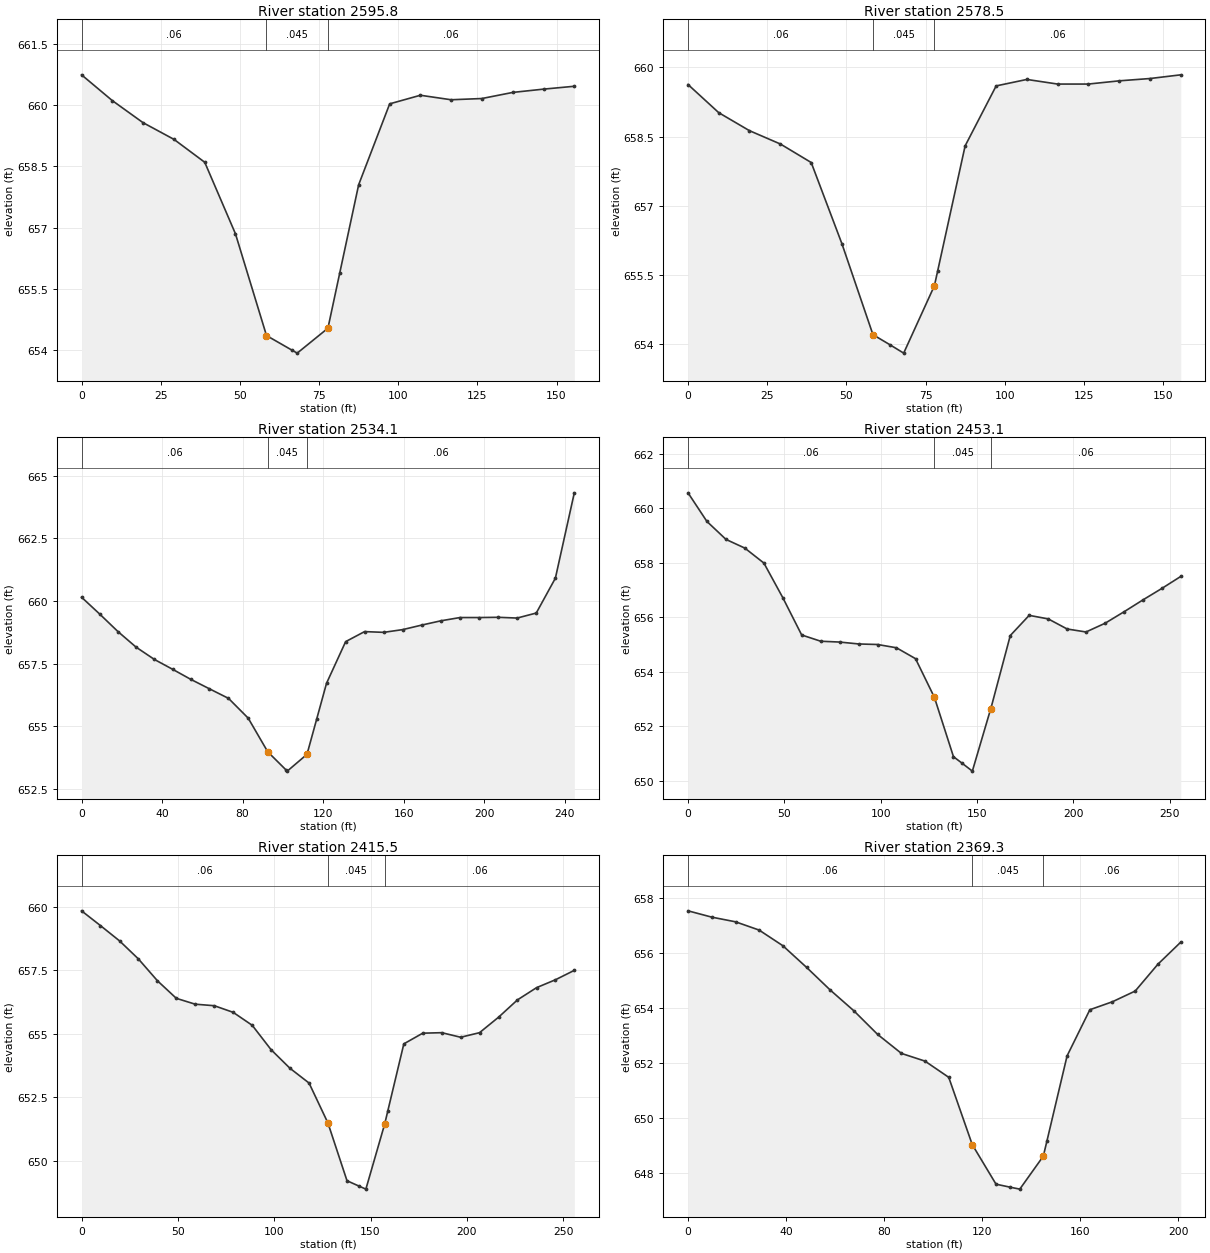
Type RM Length L Ch R = 1 ,2595.8  ,17.3,17.3,17.3
XS GIS Cut Line= 2
     1822466.133       433532.47     1822611.446      433476.741
#Sta/Elev= 19
       0  660.74     9.7  660.11    19.4  659.57    29.2  659.16    38.9   658.6
    48.6  656.85    58.4  654.36    66.5     654    68.1  653.93    77.8  654.54
    81.5  655.88    87.5  658.05    97.3  660.03     107  660.24   116.7  660.13
   126.4  660.16   136.2  660.31   145.9  660.39   155.6  660.46
#Mann= 3 , 0 , 0
       0     .06       0    58.4    .045       0    77.8     .06       0
Bank Sta=58.4,77.8
XS Rating Curve= 0 ,0
Exp/Cntr=0.3,0.1

Type RM Length L Ch R = 1 ,2578.5  ,48.4,44.4,40.9
XS GIS Cut Line= 2
     1822474.988      433547.574       1822620.3      433491.845
#Sta/Elev= 19
       0  659.63     9.7  659.02    19.4  658.63    29.2  658.34    38.9  657.94
    48.6  656.18    58.4  654.21    63.8  653.99    68.1  653.81    77.8  655.27
    78.8  655.58    87.5   658.3    97.3   659.6     107  659.74   116.7  659.64
   126.4  659.64   136.2  659.71   145.9  659.76   155.6  659.84
#Mann= 3 , 0 , 0
       0     .06       0    58.4    .045       0    77.8     .06       0
Bank Sta=58.4,77.8
XS Rating Curve= 0 ,0
Exp/Cntr=0.3,0.1

Type RM Length L Ch R = 1 ,2534.1  ,79.2,81,82.4
XS GIS Cut Line= 4
     1822468.217      433602.783     1822527.592      433580.908
     1822577.592      433550.699     1822684.883      433490.283
#Sta/Elev= 29
       0  660.15       9  659.48    18.1  658.78    27.1  658.16    36.2  657.67
    45.2  657.28    54.2  656.88    63.3  656.51      73  656.12    82.8  655.33
    92.5  653.99   101.8  653.25   102.2  653.22     112  653.89   116.8  655.29
   121.7  656.72   131.2  658.38   140.6  658.78   150.1  658.75   159.6  658.86
     169  659.04   178.5  659.21     188  659.34   197.5  659.34   206.9  659.35
   216.4  659.32   225.9  659.52   235.4  660.91   244.8  664.31
#Mann= 3 , 0 , 0
       0     .06       0    92.5    .045       0     112     .06       0
Bank Sta=92.5,112
XS Rating Curve= 0 ,0
Exp/Cntr=0.3,0.1

Type RM Length L Ch R = 1 ,2453.1  ,37.5,37.6,37.7
XS GIS Cut Line= 2
     1822484.883      433685.248      1822714.05      433571.533
#Sta/Elev= 29
       0  660.57     9.8  659.52    19.7  658.86    29.5  658.54    39.4  657.99
    49.2  656.72      59  655.35    68.9  655.12    78.7  655.09    88.6  655.02
    98.4     655   108.2  654.88   118.1  654.48   127.9  653.06   137.8  650.88
   142.1  650.65   147.6  650.35   157.1  652.63   157.4   652.7   167.3  655.33
   177.1  656.07     187  655.94   196.8  655.57   206.6  655.46   216.5  655.78
   226.3   656.2   236.2  656.64     246  657.06   255.8   657.5
#Mann= 3 , 0 , 0
       0     .06       0   127.9    .045       0   157.1     .06       0
Bank Sta=127.9,157.1
XS Rating Curve= 0 ,0
Exp/Cntr=0.3,0.1

Type RM Length L Ch R = 1 ,2415.5  ,55.7,46.2,35.9
XS GIS Cut Line= 2
     1822507.453      433714.762     1822736.619      433601.047
#Sta/Elev= 29
       0  659.83     9.8  659.25    19.7  658.65    29.5  657.94    39.4  657.08
    49.2  656.39      59  656.16    68.9   656.1    78.7  655.84    88.6  655.33
    98.4  654.37   108.2  653.64   118.1  653.06   127.9  651.49   137.8  649.22
     144  649.01   147.6  648.89   157.4  651.46     159  651.97   167.3   654.6
   177.1  655.02     187  655.04   196.8  654.86   206.6  655.04   216.5  655.65
   226.3  656.33   236.2  656.81     246  657.12   255.8  657.49
#Mann= 3 , 0 , 0
       0     .06       0   127.9    .045       0   157.4     .06       0
Bank Sta=127.9,157.4
XS Rating Curve= 0 ,0
Exp/Cntr=0.3,0.1

Type RM Length L Ch R = 1 ,2369.3  ,75,72,69.6
XS GIS Cut Line= 4
     1822566.654      433747.574     1822646.863       433713.72
     1822690.613      433662.158     1822715.613      433623.095
#Sta/Elev= 24
       0  657.54     9.7  657.31    19.4  657.14      29  656.84    38.7  656.27
    48.4  655.48      58  654.66    67.7   653.9    77.4  653.04    87.1  652.35
    96.7  652.07   106.4  651.48     116  649.03   125.7  647.59   131.5  647.48
   135.4  647.41     145  648.61   146.5  649.17   154.7  652.26     164  653.94
   173.2  654.23   182.5  654.62   191.8   655.6   201.1   656.4
#Mann= 3 , 0 , 0
       0     .06       0     116    .045       0     145     .06       0
Bank Sta=116,145
XS Rating Curve= 0 ,0
Exp/Cntr=0.3,0.1

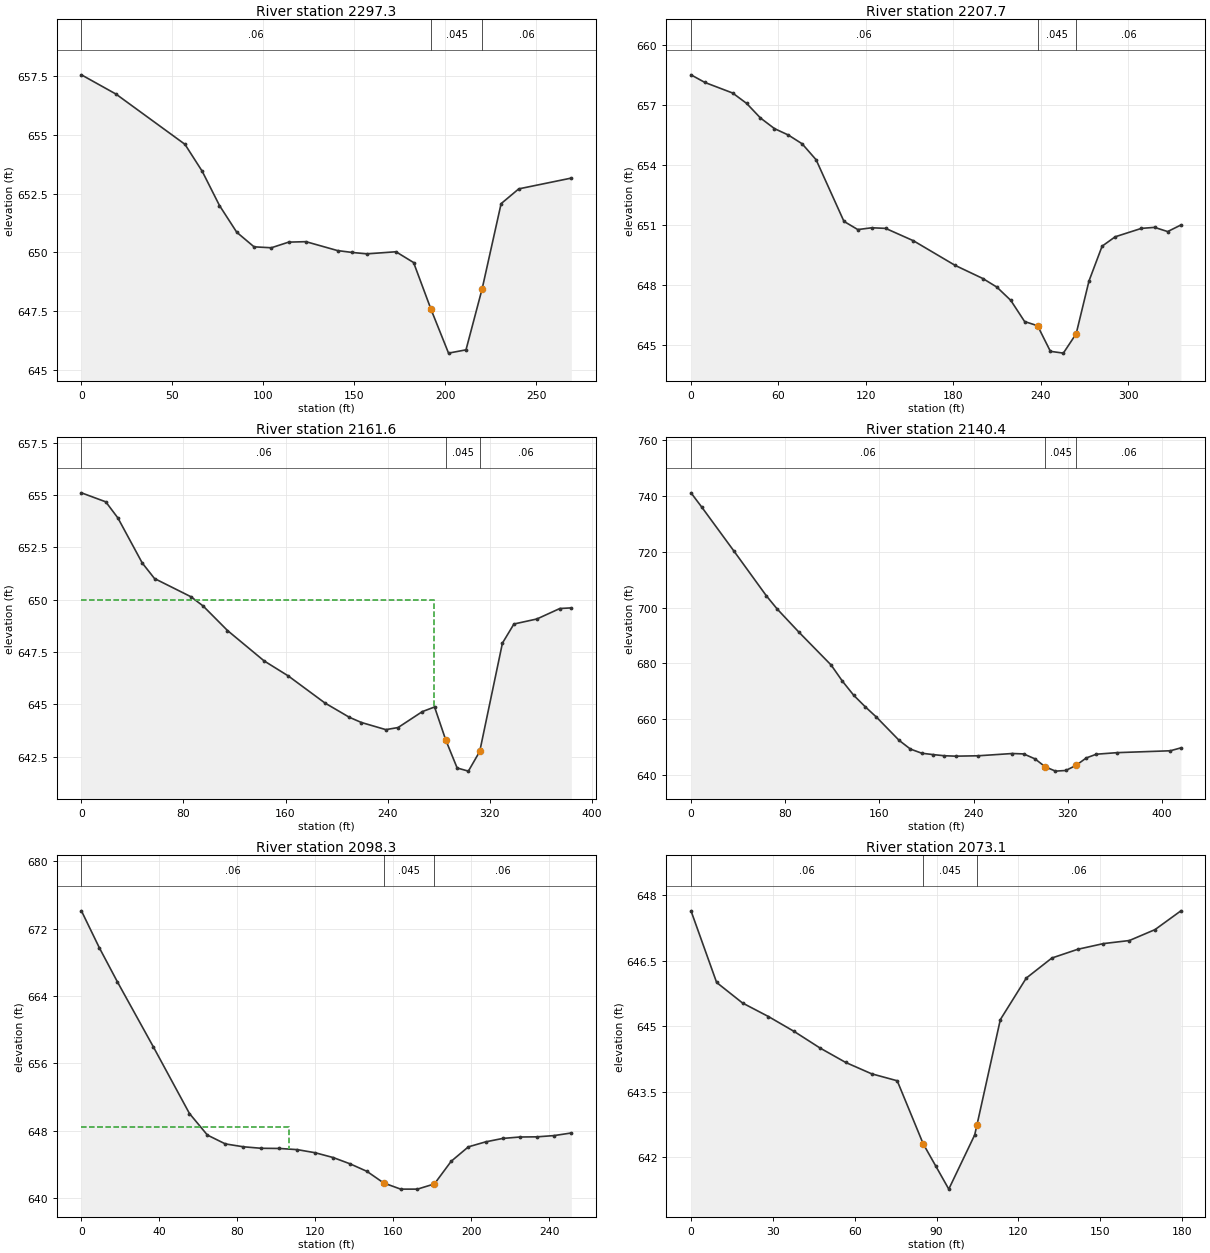
Type RM Length L Ch R = 1 ,2297.3  ,84.6,89.6,94
XS GIS Cut Line= 4
     1822578.633      433775.179     1822711.446      433777.783
     1822723.599      433739.588     1822774.814      433657.991
#Sta/Elev= 22
       0  657.56      19  656.74    56.9   654.6    66.4  653.45    75.9  651.99
    85.4  650.85    94.9  650.23   104.4  650.19   113.9  650.43   123.4  650.45
   140.8  650.07   148.9  649.99   156.9  649.93   172.9  650.02   182.6  649.56
   192.2  647.56   201.8   645.7   211.4  645.84   220.3  648.45   230.7  652.07
   240.4   652.7   269.3  653.16
#Mann= 3 , 0 , 0
       0     .06       0   192.2    .045       0   220.3     .06       0
Bank Sta=192.2,220.3
XS Rating Curve= 0 ,0
Exp/Cntr=0.3,0.1

Type RM Length L Ch R = 1 ,2207.7  ,46.1,46.1,45.8
XS GIS Cut Line= 4
      1822562.14      433789.936     1822791.133      433785.595
     1822822.383      433754.345     1822859.363      433703.304
#Sta/Elev= 30
       0  658.53     9.5  658.15    28.6  657.62    38.2   657.1    47.7  656.37
    57.3  655.84    66.8  655.52    76.3  655.08    85.9  654.28     105   651.2
   114.5  650.79   124.1  650.88   133.6  650.85   152.7  650.23   181.3     649
   200.4  648.34     210  647.91   219.5  647.25     229  646.19   237.9  645.98
   246.7   644.7   255.6  644.61   264.4  645.58   273.2  648.22   282.2  649.96
   291.2  650.43   309.2  650.85   318.2   650.9   327.2  650.69   336.3  651.02
#Mann= 3 , 0 , 0
       0     .06       0   237.9    .045       0   264.4     .06       0
Bank Sta=237.9,264.4
XS Rating Curve= 0 ,0
Exp/Cntr=0.3,0.1

Type RM Length L Ch R = 1 ,2161.6  ,20.5,21.2,22.8
XS GIS Cut Line= 4
     1822544.779      433825.526     1822821.515      433820.317
     1822852.765      433789.067     1822889.744      433738.026
#Sta/Elev= 26
       0   655.1    19.1  654.67    28.6   653.9    47.7  651.75    57.3  651.01
    85.9  650.14    95.4   649.7   114.5  648.53   143.2  647.08   162.2  646.36
   190.9  645.07     210  644.39   219.5  644.14   238.6   643.8   248.2   643.9
   267.2  644.66   276.8  644.88   285.6   643.3   294.5  641.97   303.3  641.82
   312.2  642.76     330  647.93     339  648.84     357  649.08     375  649.58
     384  649.61
#Mann= 3 , 0 , 0
       0     .06       0   285.6    .045       0   312.2     .06       0
#XS Ineff= 2 , 0
       0     276     650               0
Permanent Ineff=
       F       F
Bank Sta=285.6,312.2
XS Rating Curve= 0 ,0
Exp/Cntr=0.3,0.1

Type RM Length L Ch R = 1 ,2140.4  ,43.7,42.1,39.5
XS GIS Cut Line= 5
     1822635.057      434016.498      1822748.52      433980.572
     1822838.182       433832.47     1822882.453      433790.804
     1822918.043       433738.72
#Sta/Elev= 30
       0  741.01     9.2  735.87    36.6  720.11    64.1  704.13    73.2  699.46
    91.6  691.21     119  679.43   128.6  673.65   138.2  668.61   147.9  664.53
   157.5   660.8   176.7  652.51   186.3  649.39     196   647.9   205.6  647.41
   215.2     647   224.8  646.85     244  646.99   272.9   647.8   282.5  647.65
   292.1  645.88   300.8  643.04   309.5   641.5   318.2  641.73   326.9  643.53
   335.6  646.21   344.2  647.55     362  648.11     407  648.78     416  649.82
#Mann= 3 , 0 , 0
       0     .06       0   300.8    .045       0   326.9     .06       0
Bank Sta=300.8,326.9
XS Rating Curve= 0 ,0
Exp/Cntr=0.3,0.1

Type RM Length L Ch R = 1 ,2098.3  ,31.8,25.1,19.5
XS GIS Cut Line= 4
     1822785.057      433983.338     1822856.932      433876.047
     1822898.078      433831.776     1822928.286       433778.13
#Sta/Elev= 27
       0  674.13     9.2  669.74    18.4  665.72    36.9  657.97    55.4  650.06
    64.6   647.5    73.8  646.45      83  646.11    92.2  645.93   101.5  645.91
   110.7  645.77   119.9   645.4   129.1  644.83   137.8  644.08   146.4  643.19
     155  641.81   163.7  641.08   172.3  641.08     181   641.7   189.6  644.39
   198.4   646.1   207.2  646.69     216   647.1   224.8  647.27   233.6  647.29
   242.4  647.44   251.2  647.75
#Mann= 3 , 0 , 0
       0     .06       0     155    .045       0     181     .06       0
#XS Ineff= 2 , 0
          106.31  648.44
Permanent Ineff=
       F       F
Bank Sta=155,181
XS Rating Curve= 0 ,0
Exp/Cntr=0.3,0.1

Type RM Length L Ch R = 1 ,2073.1  ,22.6,22.6,22.6
XS GIS Cut Line= 2
     1822863.182       433946.88     1822941.828      433785.422
#Sta/Elev= 22
       0  647.64     9.4     646    18.9  645.53    28.4  645.22    37.8  644.88
    47.3   644.5    56.7  644.17    66.2  643.91    75.6  643.75    85.1  642.31
    89.8  641.79    94.5  641.27     104  642.51   104.8  642.73   113.4  645.15
   122.9   646.1   132.3  646.56   141.8  646.76   151.2  646.89   160.7  646.96
   170.1  647.21   179.6  647.64
#Mann= 3 , 0 , 0
       0     .06       0    85.1    .045       0   104.8     .06       0
Bank Sta=85.1,104.8
XS Rating Curve= 0 ,0
Exp/Cntr=0.3,0.1

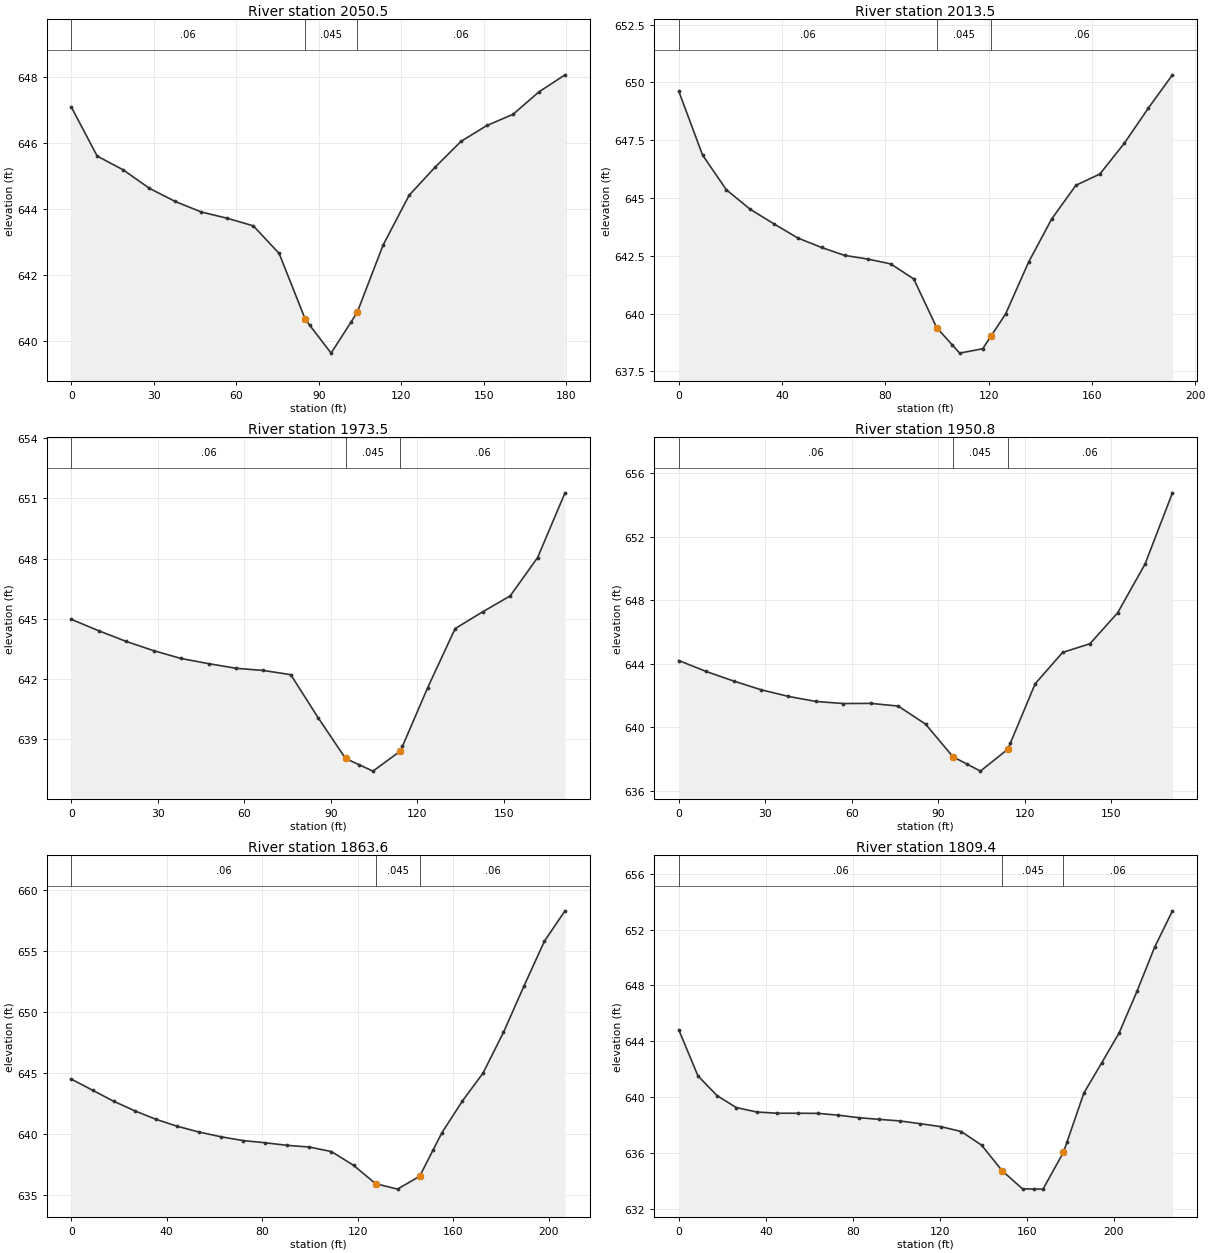
Type RM Length L Ch R = 1 ,2050.5  ,37.2,37,36.4
XS GIS Cut Line= 2
     1822885.057      433953.651     1822963.703      433792.192
#Sta/Elev= 22
       0   647.1     9.4  645.61    18.9  645.19    28.4  644.63    37.8  644.23
    47.3  643.91    56.7  643.72    66.2  643.49    75.6  642.65    85.1  640.65
    86.8  640.46    94.5  639.62   101.8  640.57     104  640.86   113.4   642.9
   122.9  644.42   132.3  645.27   141.8  646.06   151.2  646.54   160.7  646.88
   170.1  647.56   179.6  648.08
#Mann= 3 , 0 , 0
       0     .06       0    85.1    .045       0     104     .06       0
Bank Sta=85.1,104
XS Rating Curve= 0 ,0
Exp/Cntr=0.3,0.1

Type RM Length L Ch R = 1 ,2013.5  ,44.9,40,35.4
XS GIS Cut Line= 4
     1822906.411      433973.963     1822938.182      433928.651
      1822974.64      433847.401     1822988.182      433802.609
#Sta/Elev= 24
       0  649.62     9.2  646.86    18.4  645.36    27.7  644.51    36.9  643.88
    46.1  643.27    55.3  642.86    64.2  642.52    73.2  642.36    82.1  642.15
      91   641.5    99.9  639.39   105.9  638.65   108.8  638.29   117.7  638.48
   120.9  639.02   126.6  639.99   135.5  642.23   144.4  644.09   153.8  645.55
   163.1  646.04   172.5  647.36   181.8  648.88   191.2  650.33
#Mann= 3 , 0 , 0
       0     .06       0    99.9    .045       0   120.9     .06       0
Bank Sta=99.9,120.9
XS Rating Curve= 0 ,0
Exp/Cntr=0.3,0.1

Type RM Length L Ch R = 1 ,1973.5  ,22.7,22.7,22.7
XS GIS Cut Line= 2
     1822977.244      433983.859     1823016.307      433817.192
#Sta/Elev= 21
       0  644.97     9.5   644.4      19  643.87    28.5  643.41      38  643.02
    47.6  642.76    57.1  642.53    66.6  642.42    76.1  642.21    85.6  640.06
    95.1  638.03    99.8  637.72   104.6   637.4   114.1   638.4   114.8  638.63
   123.6  641.57   133.1  644.51   142.6  645.34   152.2  646.14   161.7  648.05
   171.2  651.28
#Mann= 3 , 0 , 0
       0     .06       0    95.1    .045       0   114.1     .06       0
Bank Sta=95.1,114.1
XS Rating Curve= 0 ,0
Exp/Cntr=0.3,0.1

Type RM Length L Ch R = 1 ,1950.8  ,80.9,87.2,90.9
XS GIS Cut Line= 2
      1822999.64      433987.505     1823038.703      433820.838
#Sta/Elev= 21
       0   644.2     9.5  643.51      19  642.91    28.5  642.36      38  641.94
    47.6  641.62    57.1  641.49    66.6   641.5    76.1  641.33    85.6  640.19
    95.1  638.13     100  637.67   104.6  637.23   114.1  638.61     115     639
   123.6  642.74   133.1  644.71   142.6  645.26   152.2  647.21   161.7  650.28
   171.2  654.77
#Mann= 3 , 0 , 0
       0     .06       0    95.1    .045       0   114.1     .06       0
Bank Sta=95.1,114.1
XS Rating Curve= 0 ,0
Exp/Cntr=0.3,0.1

Type RM Length L Ch R = 1 ,1863.6  ,56.3,54.2,53.9
XS GIS Cut Line= 4
     1823027.244      434017.192     1823060.578      433988.026
     1823114.744      433891.151     1823129.328      433841.672
#Sta/Elev= 25
       0  644.52     8.9  643.61    17.7  642.71    26.6  641.92    35.4  641.23
    44.3  640.66    53.5  640.18    62.8  639.79      72  639.48    81.3   639.3
    90.5  639.09    99.8  638.95     109  638.58   118.3  637.45   127.5  635.95
   136.7   635.5     146  636.56   151.7  638.74   155.3  640.12   163.9  642.73
   172.5     645   181.1  648.35   189.7  652.15   198.3  655.84   206.9  658.32
#Mann= 3 , 0 , 0
       0     .06       0   127.5    .045       0     146     .06       0
Bank Sta=127.5,146
XS Rating Curve= 0 ,0
Exp/Cntr=0.3,0.1

Type RM Length L Ch R = 1 ,1809.4  ,52.4,61.2,68.7
XS GIS Cut Line= 4
     1823077.244      434069.276      1823099.64      434055.213
     1823164.744       433909.38     1823176.203      433870.317
#Sta/Elev= 28
       0  644.81     8.8  641.51    17.6  640.09    26.4  639.24    35.8  638.92
    45.2  638.83    54.6  638.83      64  638.82    73.4  638.69    82.8  638.51
    92.2  638.39   101.6  638.28     111  638.08   120.4  637.87   129.8  637.52
   139.2  636.54   148.6  634.71     158  633.41   163.4   633.4   167.4  633.39
   176.8  636.03   178.4  636.75   186.2  640.28   194.3  642.42   202.4  644.59
   210.6  647.57   218.7  650.73   226.9  653.34
#Mann= 3 , 0 , 0
       0     .06       0   148.6    .045       0   176.8     .06       0
Bank Sta=148.6,176.8
XS Rating Curve= 0 ,0
Exp/Cntr=0.3,0.1

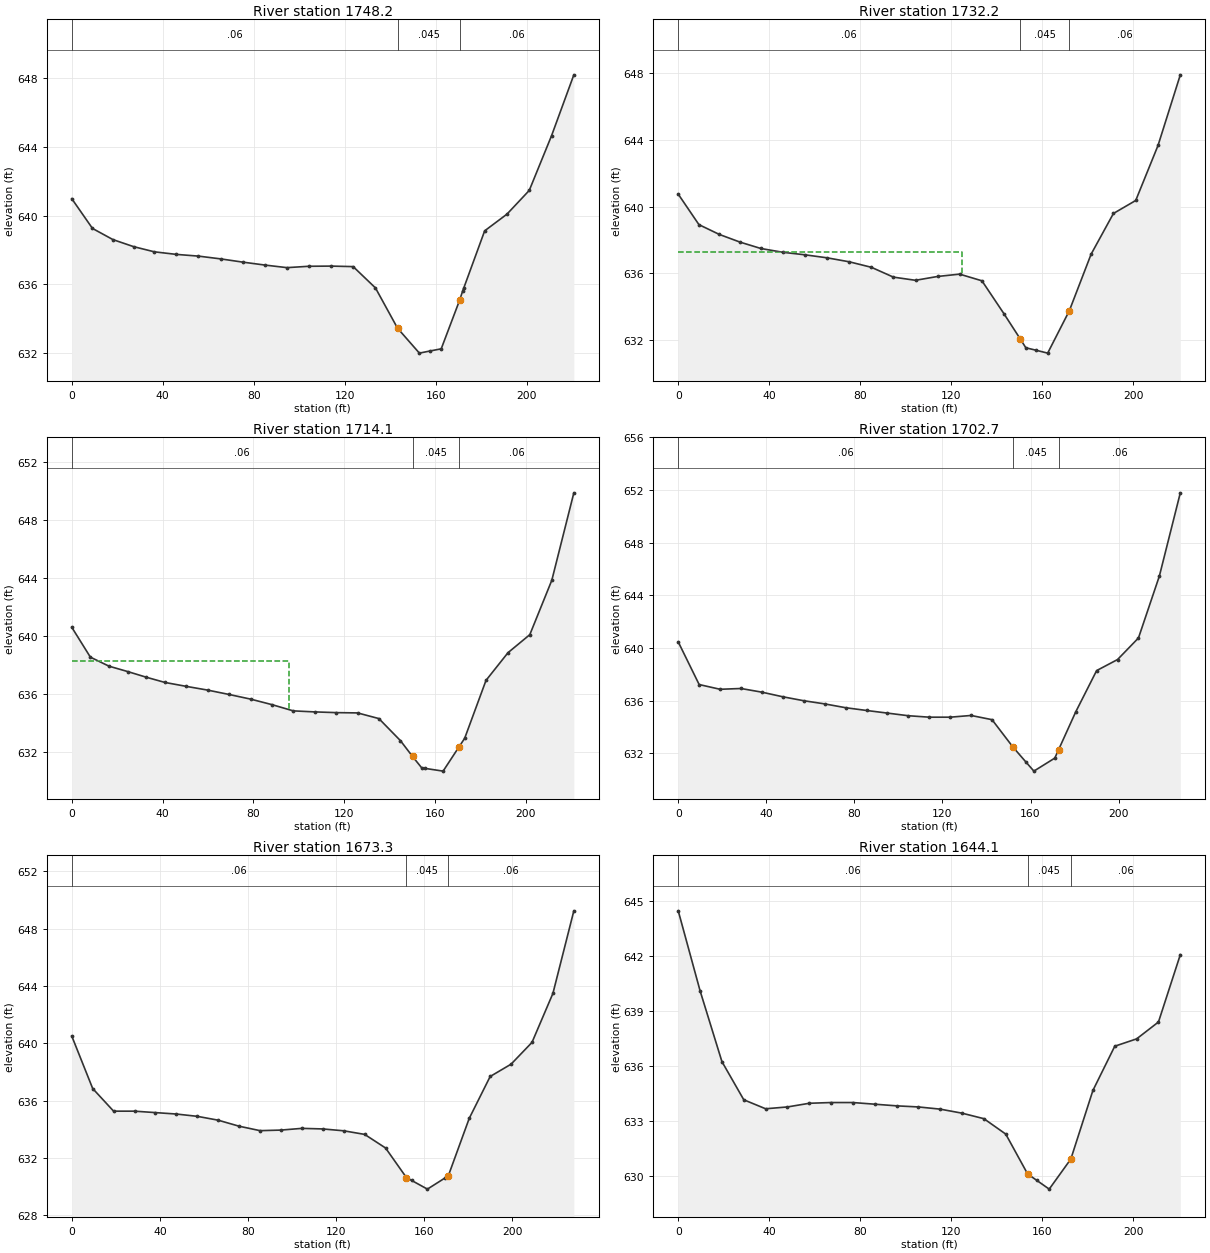
Type RM Length L Ch R = 1 ,1748.2  ,16.1,16,16.1
XS GIS Cut Line= 5
     1823116.828      434088.026     1823146.515      434067.192
     1823193.911      433971.359     1823222.036      433945.317
     1823237.661       433909.38
#Sta/Elev= 27
       0  640.98     9.1  639.25    18.1   638.6    27.2  638.19    36.3  637.89
      46  637.74    55.7  637.64    65.4  637.48    75.2  637.29    84.9  637.12
    94.6  636.97   104.3  637.05     114  637.06   123.7  637.03   133.5  635.79
   143.2  633.45   152.8     632   157.3  632.12   162.4  632.25   170.5  635.08
   171.9  635.64   172.3  635.78   181.5  639.11   191.3  640.08   201.1  641.46
   210.9  644.64   220.7  648.18
#Mann= 3 , 0 , 0
       0     .06       0   143.2    .045       0   170.5     .06       0
Bank Sta=143.2,170.5
XS Rating Curve= 0 ,0
Exp/Cntr=0.3,0.1

Type RM Length L Ch R = 1 ,1732.2  ,24.8,18,13
XS GIS Cut Line= 5
     1823129.849      434097.401     1823159.536      434076.567
     1823206.932      433980.734     1823235.057      433954.692
     1823250.682      433918.755
#Sta/Elev= 27
       0  640.76     9.1  638.93    18.1  638.34    27.2  637.88    36.3   637.5
      46  637.27    55.7  637.12    65.4  636.94    75.2   636.7    84.9  636.37
    94.6  635.78   104.3  635.59     114  635.82   123.7  635.96   133.5  635.56
   143.2  633.58  150.35  632.07   152.8  631.54   157.1   631.4   162.4  631.22
   171.9  633.76   172.1  633.83   181.5  637.16   191.3   639.6   201.1  640.38
   210.9  643.68   220.7  647.92
#Mann= 3 , 0 , 0
       0     .06       0  150.35    .045       0   171.9     .06       0
#XS Ineff= 2 , 0
          124.53   637.3
Permanent Ineff=
       F       F
Bank Sta=150.35,171.9
XS Rating Curve= 0 ,0
Exp/Cntr=0.3,0.1

Type RM Length L Ch R = 1 ,1714.1  ,12.3,11.5,10.8
XS GIS Cut Line= 4
     1823147.036      434110.422     1823178.286      434083.859
     1823246.515      433959.901     1823263.182      433925.005
#Sta/Elev= 28
       0  640.61     8.2  638.55    16.4  637.93    24.6  637.56    32.8  637.17
      41  636.81    50.4  636.54    59.9  636.28    69.3  635.98    78.8  635.66
    88.2  635.28    97.6  634.85     107  634.78   116.5  634.73   125.9  634.71
   135.3  634.32   144.8   632.8  150.13  631.71   154.2  630.92   155.6  630.89
   163.6   630.7   170.6  632.37   173.1  632.96   182.5  636.95   192.2  638.86
   201.8   640.1   211.5  643.85   221.2  649.87
#Mann= 3 , 0 , 0
       0     .06       0  150.13    .045       0   170.6     .06       0
#XS Ineff= 2 , 0
           95.84  638.32
Permanent Ineff=
       F       F
Bank Sta=150.13,170.6
XS Rating Curve= 0 ,0
Exp/Cntr=0.3,0.1

Type RM Length L Ch R = 1 ,1702.7  ,29.4,29.4,29.5
XS GIS Cut Line= 2
     1823172.036      434131.255      1823274.64      433927.609
#Sta/Elev= 27
       0  640.46     9.5  637.22      19  636.86    28.5  636.92      38  636.64
    47.5  636.29      57  635.99    66.5  635.75      76  635.46    85.5  635.25
      95  635.05   104.5  634.85     114  634.74   123.5  634.74     133  634.87
   142.5  634.55     152  632.47   157.7  631.37   161.5  630.64     171  631.63
   172.7  632.26   180.5  635.14     190  638.28   199.5  639.12     209  640.76
   218.5  645.47     228  651.79
#Mann= 3 , 0 , 0
       0     .06       0     152    .045       0   172.7     .06       0
Bank Sta=152,172.7
XS Rating Curve= 0 ,0
Exp/Cntr=0.3,0.1

Type RM Length L Ch R = 1 ,1673.3  ,29.4,29.2,28.8
XS GIS Cut Line= 2
     1823200.161       434140.63     1823302.765      433936.984
#Sta/Elev= 27
       0   640.5     9.5  636.84      19  635.26    28.5  635.26      38  635.16
    47.5  635.06      57   634.9    66.5  634.63      76  634.21    85.5   633.9
      95  633.94   104.5  634.06     114  634.02   123.5  633.89     133  633.64
   142.5  632.69     152  630.62   154.3  630.43   161.5  629.82   169.3  630.58
     171  630.75   180.5  634.76     190  637.68   199.5  638.54     209  640.06
   218.5  643.48     228  649.24
#Mann= 3 , 0 , 0
       0     .06       0     152    .045       0     171     .06       0
Bank Sta=152,171
XS Rating Curve= 0 ,0
Exp/Cntr=0.3,0.1

Type RM Length L Ch R = 1 ,1644.1  ,30.3,30.4,30.3
XS GIS Cut Line= 2
     1823228.286      434154.692      1823324.64      433956.255
#Sta/Elev= 25
       0  644.45     9.6  640.09    19.2  636.23    28.8  634.15    38.4  633.66
      48  633.76    57.6  633.96    67.1     634    76.7     634    86.3  633.91
    95.9  633.82   105.5  633.76   115.1  633.64   124.7  633.42   134.3  633.12
   143.9  632.28   153.5  630.11   157.5  629.76     163  629.28   172.5  630.92
   182.2  634.66   191.8  637.07   201.4  637.47     211  638.39   220.6  642.06
#Mann= 3 , 0 , 0
       0     .06       0   153.5    .045       0   172.5     .06       0
Bank Sta=153.5,172.5
XS Rating Curve= 0 ,0
Exp/Cntr=0.3,0.1

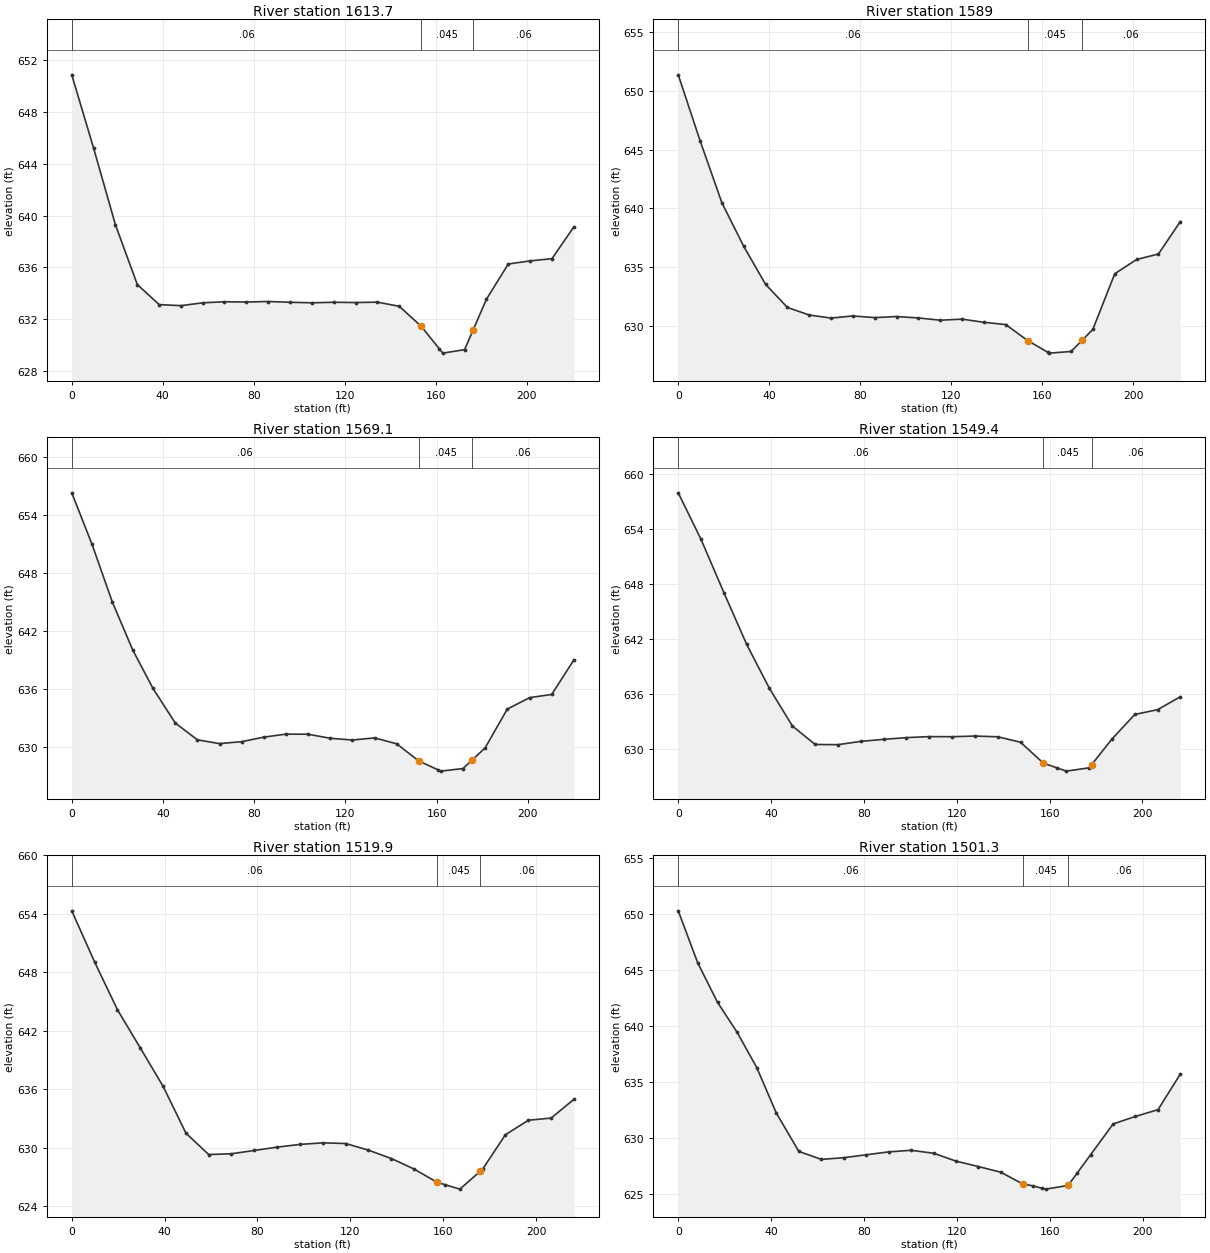
Type RM Length L Ch R = 1 ,1613.7  ,24.8,24.7,24.8
XS GIS Cut Line= 2
     1823254.849      434169.276     1823351.203      433970.838
#Sta/Elev= 26
       0  650.88     9.6  645.21    19.2  639.28    28.8  634.67    38.4  633.12
      48  633.04    57.6  633.26    67.1  633.34    76.7  633.32    86.3  633.36
    95.9   633.3   105.5  633.26   115.1   633.3   124.7  633.28   134.3  633.31
   143.9  632.99   153.5  631.45   161.4  629.72     163  629.37   172.6  629.64
   176.4  631.18   182.2  633.54   191.8  636.26   201.4   636.5     211  636.67
   220.6  639.13
#Mann= 3 , 0 , 0
       0     .06       0   153.5    .045       0   176.4     .06       0
Bank Sta=153.5,176.4
XS Rating Curve= 0 ,0
Exp/Cntr=0.3,0.1

Type RM Length L Ch R = 1 ,1589    ,20.3,19.9,19.6
XS GIS Cut Line= 2
     1823277.244      434179.692     1823373.599      433981.255
#Sta/Elev= 26
       0  651.36     9.6  645.76    19.2  640.47    28.8  636.77    38.4  633.54
      48  631.58    57.6  630.94    67.1  630.68    76.7  630.86    86.3  630.72
    95.9  630.81   105.5  630.69   115.1   630.5   124.7  630.59   134.3  630.32
   143.9  630.13   153.5  628.77   162.4  627.77     163   627.7   172.6  627.84
   177.4  628.78   182.2  629.73   191.8  634.45   201.4  635.66     211  636.13
   220.6  638.89
#Mann= 3 , 0 , 0
       0     .06       0   153.5    .045       0   177.4     .06       0
Bank Sta=153.5,177.4
XS Rating Curve= 0 ,0
Exp/Cntr=0.3,0.1

Type RM Length L Ch R = 1 ,1569.1  ,20,19.7,19.3
XS GIS Cut Line= 3
     1823306.411      434189.588     1823313.703      434154.692
     1823391.828      433987.505
#Sta/Elev= 26
       0  656.31     8.9  650.97    17.8     645    26.7  640.06    35.6  636.07
    45.4  632.48    55.1  630.74    64.8  630.35    74.5  630.55    84.2  631.02
    93.9  631.33   103.6  631.32   113.4   630.9   123.1  630.72   132.8  630.94
   142.5  630.33   152.2  628.55   160.6  627.64   161.9   627.5   171.6  627.77
   175.6  628.65   181.3  629.91     191  633.92   200.8  635.11   210.5  635.44
   220.2  639.01
#Mann= 3 , 0 , 0
       0     .06       0   152.2    .045       0   175.6     .06       0
Bank Sta=152.2,175.6
XS Rating Curve= 0 ,0
Exp/Cntr=0.3,0.1

Type RM Length L Ch R = 1 ,1549.4  ,29.5,29.5,29.5
XS GIS Cut Line= 2
     1823317.869      434198.442     1823406.411      434001.047
#Sta/Elev= 25
       0  657.94     9.8  652.87    19.7  647.03    29.5  641.38    39.3  636.58
    49.2  632.47      59  630.46    68.8  630.44    78.7   630.8    88.5  631.02
    98.3  631.21   108.2  631.32     118  631.31   127.8  631.38   137.7   631.3
   147.5   630.7   157.3  628.42   163.1  627.91   167.2  627.55     177  627.91
   178.1  628.26   186.8  631.04   196.7  633.74   206.5  634.26   216.3  635.67
#Mann= 3 , 0 , 0
       0     .06       0   157.3    .045       0   178.1     .06       0
Bank Sta=157.3,178.1
XS Rating Curve= 0 ,0
Exp/Cntr=0.3,0.1

Type RM Length L Ch R = 1 ,1519.9  ,18.9,18.6,18.2
XS GIS Cut Line= 2
     1823345.994      434207.817     1823434.536      434010.422
#Sta/Elev= 25
       0  654.31     9.8  649.08    19.7  644.15    29.5  640.25    39.3  636.32
    49.2  631.49      59   629.3    68.8  629.38    78.7  629.72    88.5  630.06
    98.3  630.34   108.2   630.5     118  630.43   127.8  629.75   137.7  628.89
   147.5  627.81   157.3  626.46     161  626.19   167.2  625.75     176  627.59
     177   627.8   186.8  631.33   196.7  632.82   206.5  633.04   216.3  634.96
#Mann= 3 , 0 , 0
       0     .06       0   157.3    .045       0     176     .06       0
Bank Sta=157.3,176
XS Rating Curve= 0 ,0
Exp/Cntr=0.3,0.1

Type RM Length L Ch R = 1 ,1501.3  ,19.7,18.5,17.3
XS GIS Cut Line= 3
     1823366.307      434210.248     1823384.363      434172.054
     1823453.113      434012.331
#Sta/Elev= 27
       0  650.27     8.4  645.63    16.9  642.12    25.4  639.43    33.8   636.3
    42.2  632.26    51.9  628.83    61.6  628.12    71.2  628.27    80.9  628.53
    90.6  628.79   100.2  628.93   109.9  628.67   119.5  627.97   129.2  627.48
   138.8  626.98   148.5  625.91  152.57  625.77   156.6  625.54   158.2  625.47
   167.8   625.8   171.6  626.87   177.5  628.54   187.2  631.28   196.8  631.95
   206.5  632.55   216.1  635.72
#Mann= 3 , 0 , 0
       0     .06       0   148.5    .045       0   167.8     .06       0
Bank Sta=148.5,167.8
XS Rating Curve= 0 ,0
Exp/Cntr=0.3,0.1

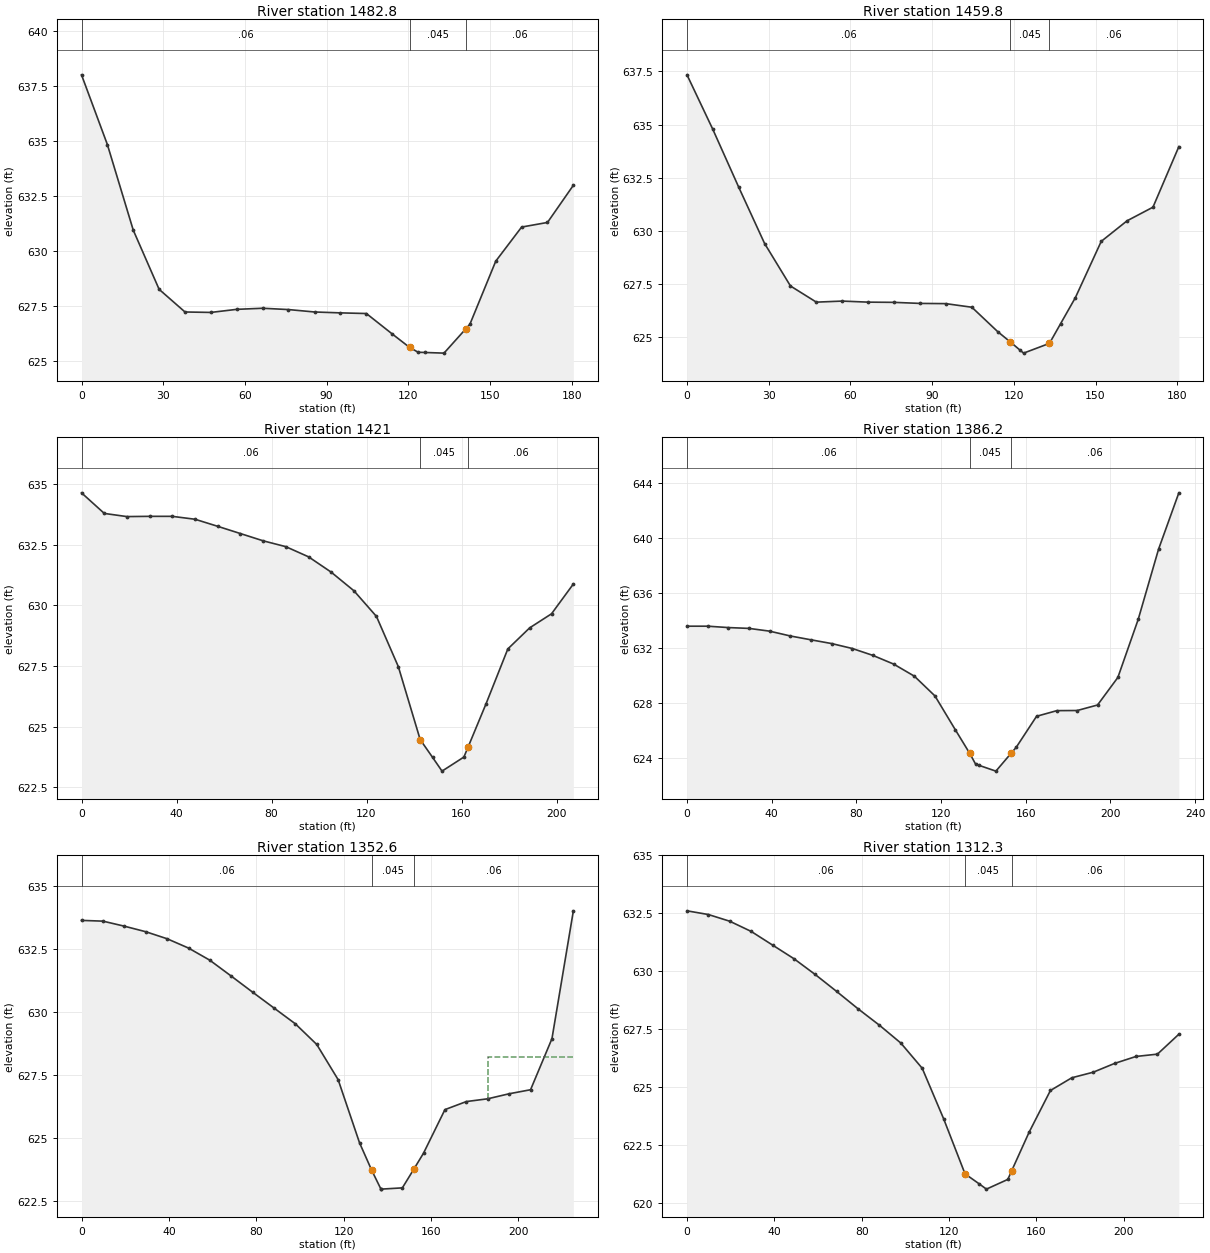
Type RM Length L Ch R = 1 ,1482.8  ,23,22.9,23
XS GIS Cut Line= 2
     1823403.807      434191.498     1823466.307      434022.054
#Sta/Elev= 23
       0  638.02     9.5  634.85      19  630.96    28.5  628.27      38  627.24
    47.5  627.22      57  627.36    66.5  627.41      76  627.35    85.6  627.24
      95   627.2   104.6  627.17   114.1  626.24  120.46  625.63   123.6  625.41
     126   625.4   133.1  625.37     141  626.46   142.6  626.68   152.1  629.55
   161.6   631.1   171.1  631.31   180.6     633
#Mann= 3 , 0 , 0
       0     .06       0  120.46    .045       0     141     .06       0
Bank Sta=120.46,141
XS Rating Curve= 0 ,0
Exp/Cntr=0.3,0.1

Type RM Length L Ch R = 1 ,1459.8  ,38.8,38.8,38.7
XS GIS Cut Line= 2
     1823426.724      434195.665     1823489.224       434026.22
#Sta/Elev= 23
       0  637.34     9.5  634.77      19  632.05    28.5   629.4      38   627.4
    47.5  626.64      57  626.69    66.5  626.64      76  626.63    85.6  626.58
      95  626.57   104.6   626.4   114.1  625.25  118.69  624.77   122.2  624.39
   123.6  624.24   133.1   624.7   137.2  625.63   142.6  626.85   152.1   629.5
   161.6  630.47   171.1  631.11   180.6  633.96
#Mann= 3 , 0 , 0
       0     .06       0  118.69    .045       0   133.1     .06       0
Bank Sta=118.69,133.1
XS Rating Curve= 0 ,0
Exp/Cntr=0.3,0.1

Type RM Length L Ch R = 1 ,1421    ,32.9,34.9,36.7
XS GIS Cut Line= 3
     1823485.751      434237.331     1823498.251       434113.72
     1823526.724      434035.942
#Sta/Elev= 25
       0  634.64     9.6  633.79    19.1  633.66    28.7  633.67    38.2  633.67
    47.8  633.55    57.3  633.26    66.9  632.96    76.5  632.66      86  632.42
    95.6     632   105.1  631.37   114.7   630.6   124.2  629.54   133.4  627.47
   142.6  624.46   147.8  623.73   151.8  623.16     161  623.74   162.8  624.16
   170.3  625.93   179.5   628.2   188.7  629.07   197.9  629.65   207.1  630.88
#Mann= 3 , 0 , 0
       0     .06       0   142.6    .045       0   162.8     .06       0
Bank Sta=142.6,162.8
XS Rating Curve= 0 ,0
Exp/Cntr=0.3,0.1

Type RM Length L Ch R = 1 ,1386.2  ,32.6,33.6,34.6
XS GIS Cut Line= 3
     1823498.251      434231.081      1823530.89      434118.581
     1823579.104      434014.006
#Sta/Elev= 28
       0   633.6     9.8   633.6    19.5   633.5    29.3  633.44      39  633.24
    48.8  632.89    58.6  632.61    68.3  632.34    78.1  631.98    87.8  631.48
    97.6  630.85   107.4  629.97   117.1  628.54   126.7  626.09  133.53  624.37
   136.3  623.59   138.1  623.49   145.9  623.08   153.1  624.38   155.5  624.81
   165.1  627.06   174.7  627.47   184.3  627.48   193.9  627.88   203.5  629.88
   213.1  634.09   222.7  639.18   232.3  643.28
#Mann= 3 , 0 , 0
       0     .06       0  133.53    .045       0   153.1     .06       0
Bank Sta=133.53,153.1
XS Rating Curve= 0 ,0
Exp/Cntr=0.3,0.1

Type RM Length L Ch R = 1 ,1352.6  ,40.3,40.3,40.3
XS GIS Cut Line= 2
     1823507.974      434231.776     1823611.446      434031.776
#Sta/Elev= 27
       0  633.64     9.8  633.61    19.6  633.41    29.4  633.19    39.2  632.91
      49  632.54    58.7  632.06    68.5  631.43    78.3  630.79    88.1  630.16
    97.9  629.53   107.7  628.71   117.5  627.31   127.3   624.8  132.86  623.71
   137.1  622.96   137.2  622.96   146.9  623.01   152.2  623.76   156.6  624.39
   166.4  626.12   176.2  626.44     186  626.55   195.8  626.75   205.6  626.91
   215.4  628.94   225.2  634.02
#Mann= 3 , 0 , 0
       0     .06       0  132.86    .045       0   152.2     .06       0
#XS Ineff= 2 , 0
                          186.32          628.23
Permanent Ineff=
       F       F
Bank Sta=132.86,152.2
XS Rating Curve= 0 ,0
Exp/Cntr=0.3,0.1

Type RM Length L Ch R = 1 ,1312.3  ,58.8,61.4,63.8
XS GIS Cut Line= 2
     1823545.474      434247.054     1823648.946      434047.054
#Sta/Elev= 26
       0  632.61     9.8  632.45    19.6  632.16    29.4  631.72    39.2  631.13
      49  630.54    58.7  629.86    68.5  629.13    78.3  628.38    88.1  627.67
    97.9   626.9   107.7  625.81   117.5  623.63   127.3  621.25   133.6  620.83
   137.1  620.59   146.9  621.01   148.6  621.37   156.6  623.04   166.4  624.85
   176.2   625.4     186  625.64   195.8  626.02   205.6  626.32   215.4  626.42
   225.2  627.28
#Mann= 3 , 0 , 0
       0     .06       0   127.3    .045       0   148.6     .06       0
Bank Sta=127.3,148.6
XS Rating Curve= 0 ,0
Exp/Cntr=0.3,0.1