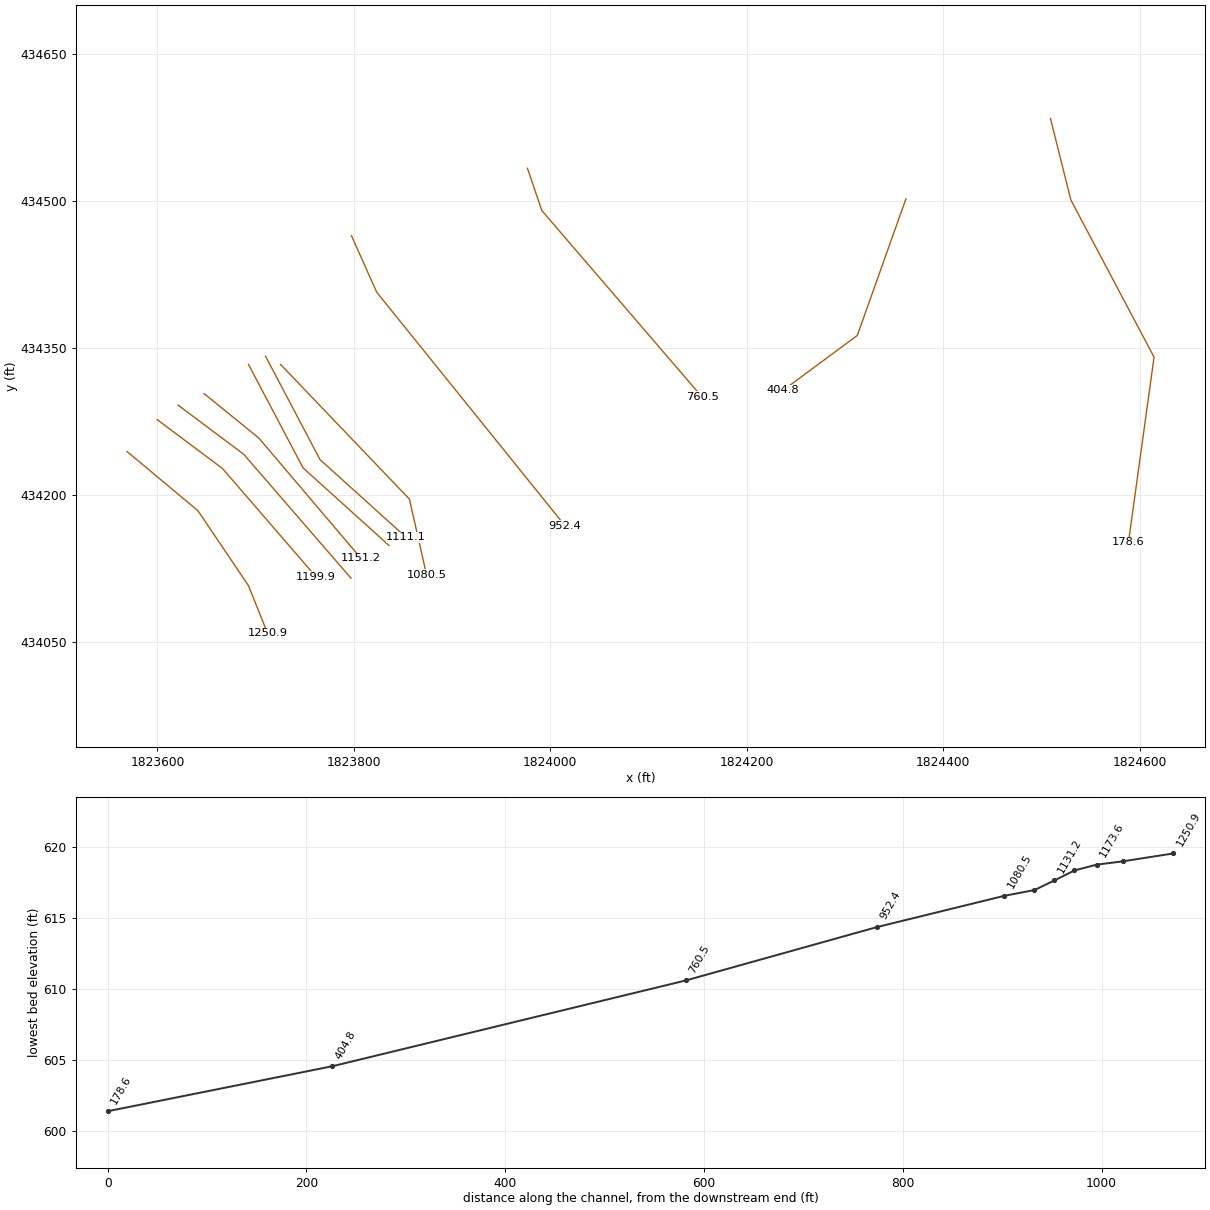
HEC-RAS study LITTLECK.prj: LITTLECK

--- LITTLECK.g01 (geometry) --- (continued)

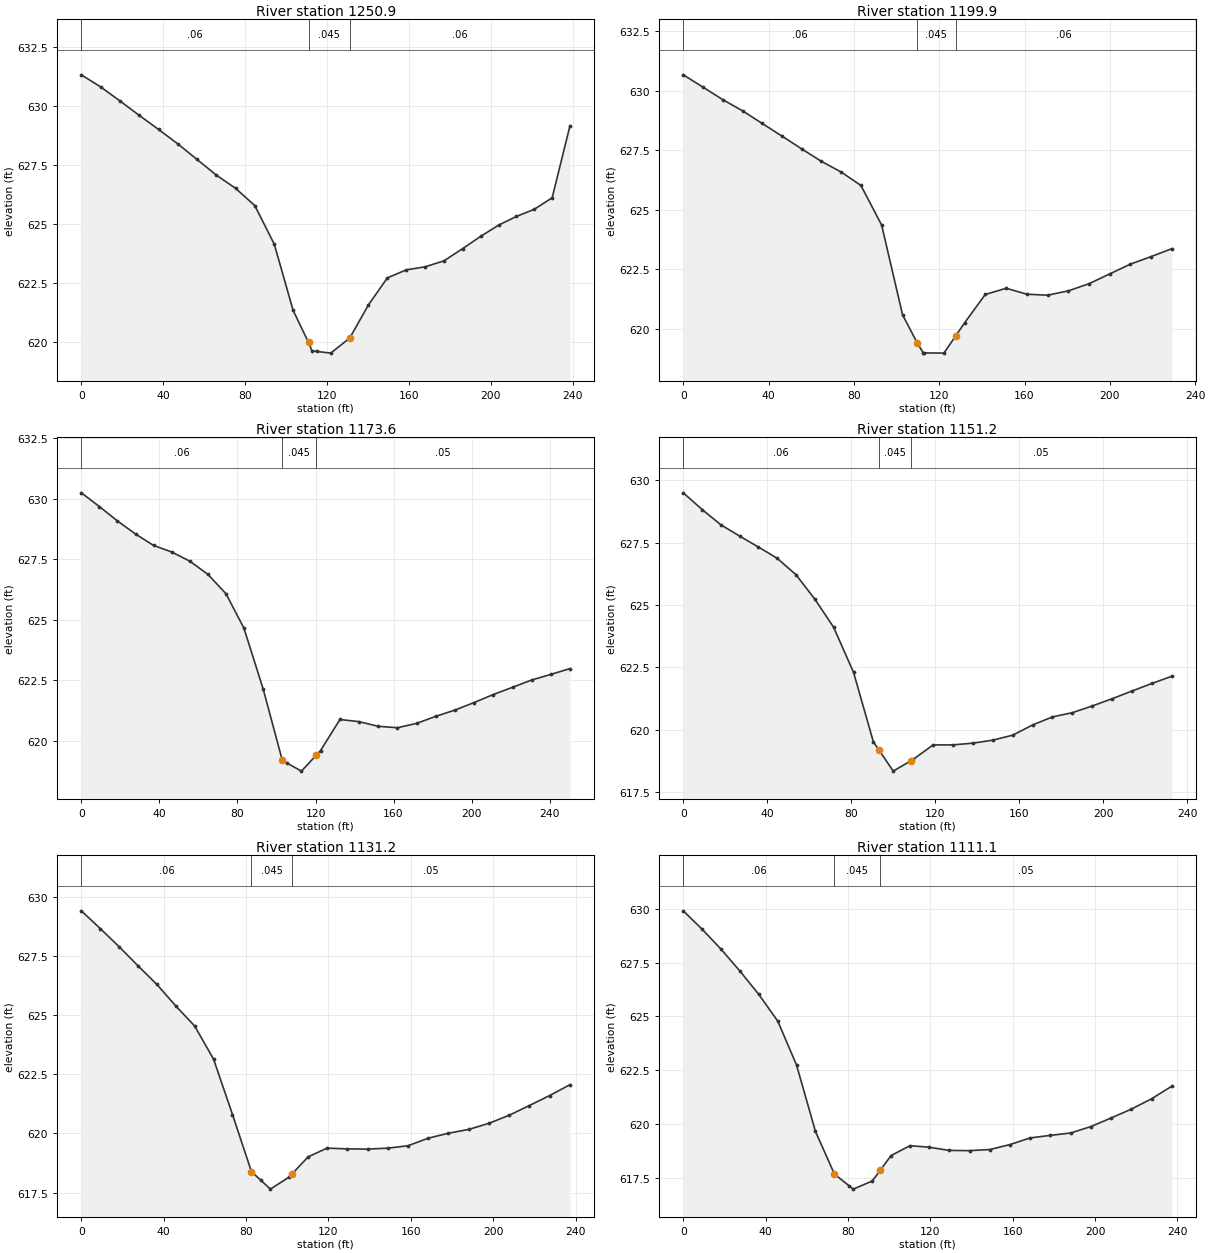
Type RM Length L Ch R = 1 ,1250.9  ,48.1,51,53.7
XS GIS Cut Line= 4
     1823569.085      434244.276     1823641.307      434183.859
     1823692.696       434107.47      1823712.14      434058.859
#Sta/Elev= 30
       0  631.32     9.4  630.81    18.8  630.22    28.2  629.61    37.7  629.01
    47.1   628.4    56.5  627.74    65.9  627.08    75.3  626.52    84.7  625.79
    94.2  624.16   103.4  621.36  110.94     620   112.6  619.65   115.2  619.62
   121.8  619.55   130.2  620.13     131  620.18   140.2  621.59   149.4  622.73
   158.6  623.07   167.8   623.2     177  623.45   186.2  623.97     195  624.49
   203.7  624.96   212.4  625.33   221.1  625.63   229.9  626.12   238.6  629.17
#Mann= 3 , 0 , 0
       0     .06       0  110.94    .045       0     131     .06       0
Bank Sta=110.94,131
XS Rating Curve= 0 ,0
Exp/Cntr=0.3,0.1

Type RM Length L Ch R = 1 ,1199.9  ,26.1,26.2,26.1
XS GIS Cut Line= 3
      1823599.64      434276.915     1823666.307      434226.915
     1823761.446      434116.498
#Sta/Elev= 28
       0  630.66     9.3  630.14    18.5  629.62    27.8  629.15      37  628.62
    46.3  628.09    55.6  627.55    64.8  627.03    74.1  626.58    83.3  626.02
      93  624.36   102.8   620.6  109.61  619.43   112.5     619   112.7     619
   122.2  618.99   127.7  619.71   131.9  620.26   141.6  621.45   151.4  621.71
   161.1  621.46   170.8  621.42   180.5   621.6   190.2   621.9   199.9  622.31
   209.6  622.72   219.4  623.04   229.1  623.37
#Mann= 3 , 0 , 0
       0     .06       0  109.61    .045       0   127.7     .06       0
Bank Sta=109.61,127.7
XS Rating Curve= 0 ,0
Exp/Cntr=0.3,0.1

Type RM Length L Ch R = 1 ,1173.6  ,22.6,22.4,22.2
XS GIS Cut Line= 3
     1823621.168      434291.498     1823687.835      434241.498
     1823797.072      434115.048
#Sta/Elev= 29
       0  630.24     9.3  629.67    18.5  629.08    27.8  628.54      37  628.07
    46.3   627.8    55.6  627.42    64.8  626.88    74.1  626.08    83.3  624.66
    93.2  622.14     103   619.2   105.4  619.09   112.8  618.76   120.4  619.42
   122.6  619.61   132.5  620.89   142.3   620.8   152.1  620.61     162  620.55
   171.8  620.73   181.6  621.02   191.5  621.28   201.3  621.59   211.1  621.92
     221  622.22   230.8  622.52   240.6  622.75   250.4  622.99
#Mann= 3 , 0 , 0
       0     .06       0     103    .045       0   120.4     .05       0
Bank Sta=103,120.4
XS Rating Curve= 0 ,0
Exp/Cntr=0.3,0.1

Type RM Length L Ch R = 1 ,1151.2  ,25.3,20.1,15.1
XS GIS Cut Line= 3
     1823647.557      434303.304     1823703.113      434258.165
     1823807.279      434135.248
#Sta/Elev= 28
       0  629.49       9  628.82    17.9  628.21    26.8  627.76    35.8  627.32
    44.7  626.87    53.7  626.21    62.6  625.24    71.6  624.11    81.1   622.3
    90.5  619.53    93.3  619.18     100  618.35   108.3  618.76   109.5  618.82
     119   619.4   128.4   619.4   137.9  619.47   147.4  619.59   156.9  619.79
   166.4   620.2   175.8  620.52   185.3  620.69   194.8  620.96   204.3  621.25
   213.8  621.56   223.2  621.86   232.7  622.15
#Mann= 3 , 0 , 0
       0     .06       0    93.3    .045       0   108.3     .05       0
Bank Sta=93.3,108.3
XS Rating Curve= 0 ,0
Exp/Cntr=0.3,0.1

Type RM Length L Ch R = 1 ,1131.2  ,20.6,20.1,20.1
XS GIS Cut Line= 3
     1823692.696      434333.165     1823748.251      434227.609
     1823835.751      434148.442
#Sta/Elev= 28
       0   629.4     9.2  628.65    18.4  627.88    27.5  627.08    36.7  626.29
    45.9  625.38      55  624.54    64.2  623.14    73.4   620.8    82.6  618.39
    87.1  618.03    91.8  617.65   100.9  618.16   102.1  618.27   110.1  619.01
   119.3  619.38   129.1  619.35     139  619.34   148.8  619.38   158.6  619.48
   168.4   619.8   178.3  620.01   188.1  620.17     198  620.43   207.8  620.77
   217.6  621.18   227.4   621.6   237.3  622.06
#Mann= 3 , 0 , 0
       0     .06       0    82.6    .045       0   102.1     .05       0
Bank Sta=82.6,102.1
XS Rating Curve= 0 ,0
Exp/Cntr=0.3,0.1

Type RM Length L Ch R = 1 ,1111.1  ,24.3,30.6,37.1
XS GIS Cut Line= 3
     1823710.057      434341.498     1823765.613      434235.942
     1823853.113      434156.776
#Sta/Elev= 28
       0  629.91     9.2  629.05    18.4  628.12    27.5  627.11    36.7  626.02
    45.9  624.78      55  622.74    64.2  619.65    73.4  617.67    80.6  617.12
    82.6  616.97    91.8  617.35    95.6  617.84   100.9  618.53   110.1  618.99
   119.3  618.92   129.1  618.77     139  618.76   148.8  618.81   158.6  619.04
   168.4  619.35   178.3  619.47   188.1  619.58     198  619.88   207.8  620.28
   217.6  620.69   227.4  621.17   237.3  621.76
#Mann= 3 , 0 , 0
       0     .06       0    73.4    .045       0    95.6     .05       0
Bank Sta=73.4,95.6
XS Rating Curve= 0 ,0
Exp/Cntr=0.3,0.1

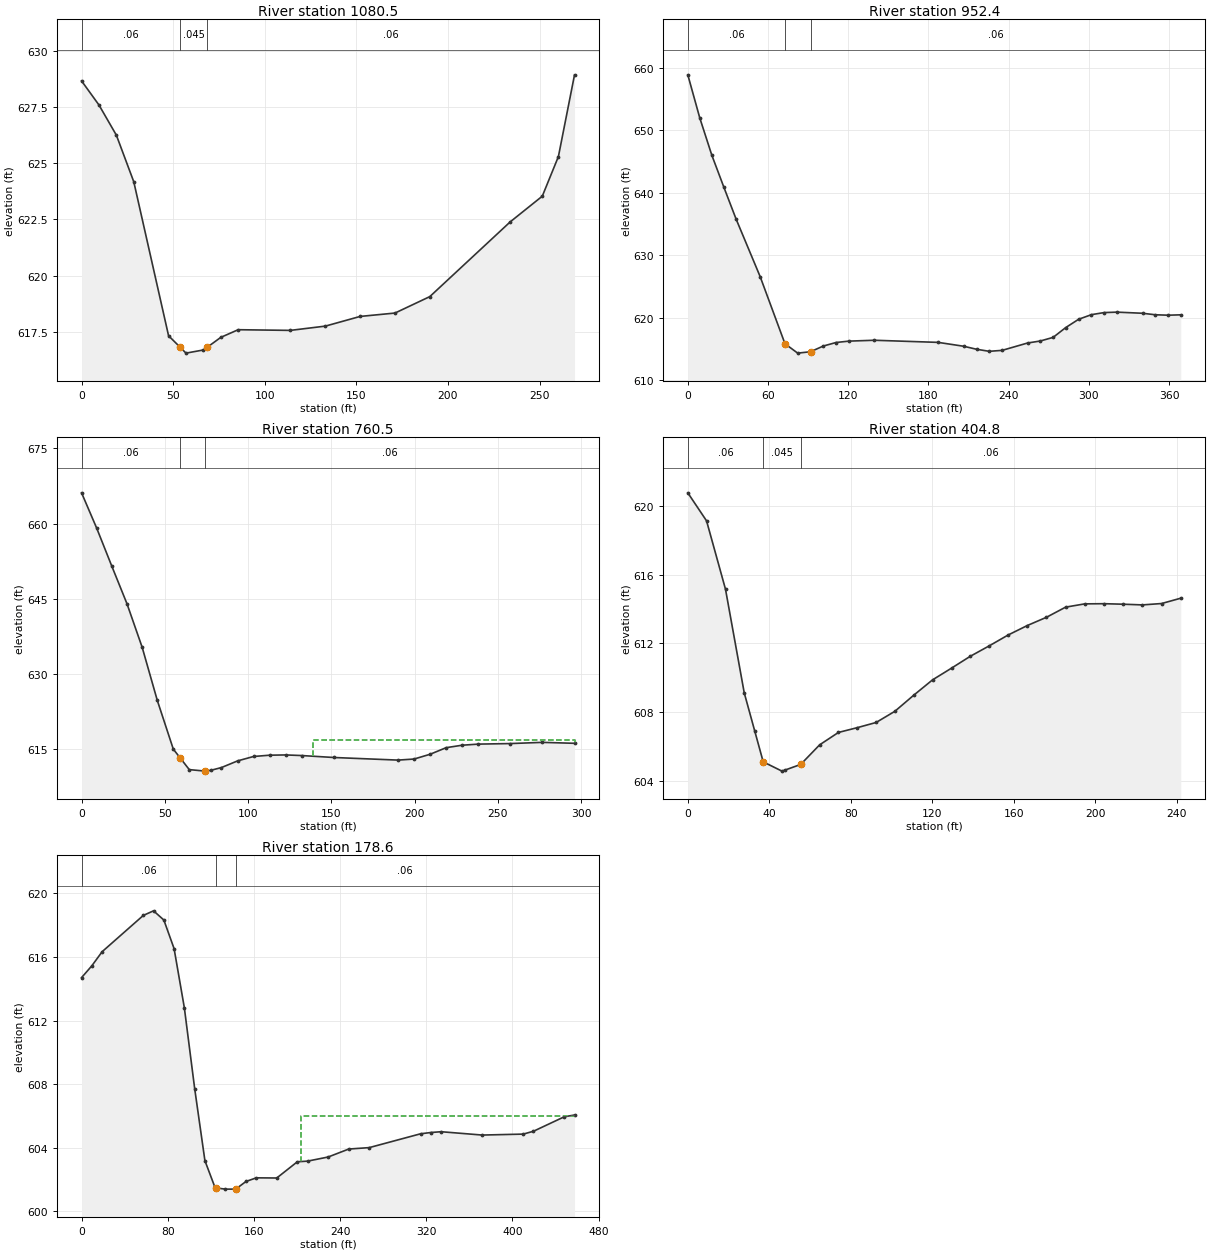
Type RM Length L Ch R = 1 ,1080.5  ,131.6,128.1,126.1
XS GIS Cut Line= 3
     1823725.335      434333.165     1823856.585      434195.665
     1823873.946      434118.581
#Sta/Elev= 20
       0  628.65     9.5  627.58      19  626.24    28.5  624.17    47.5  617.33
    53.6  616.84      57  616.56    66.5   616.7    68.6  616.82      76  617.26
    85.5   617.6     114  617.57   133.1  617.76   152.1  618.19   171.1  618.34
   190.1  619.07     234  622.39   251.5  623.53   260.3  625.29   269.1  628.92
#Mann= 3 , 0 , 0
       0     .06       0    53.6    .045       0    68.6     .06       0
Bank Sta=53.6,68.6
XS Rating Curve= 0 ,0
Exp/Cntr=0.3,0.1

Type RM Length L Ch R = 1 ,952.4   ,189.4,191.9,192.6
XS GIS Cut Line= 3
     1823797.557      434464.415     1823823.251      434406.776
     1824014.918      434168.581
#Sta/Elev= 30
       0   658.9       9  651.97      18  646.02      27   640.9    36.1  635.83
    54.1  626.62    72.7  615.86    82.2  614.36    91.8  614.58   101.3  615.49
   110.9  616.06   120.4  616.28   139.5  616.42   187.3  616.08   206.4  615.46
     216  614.98   225.5  614.65   235.1   614.8   254.2  615.98   263.7   616.3
   273.3  616.88   282.8  618.46   292.4  619.78     302  620.52   311.5  620.85
   321.1  620.92   340.2  620.74   349.7   620.5   359.3  620.43   368.8  620.49
#Mann= 3 , 0 , 0
       0     .06       0    72.7    .045       0    91.8     .06       0
Bank Sta=72.7,91.8
XS Rating Curve= 0 ,0
Exp/Cntr=0.3,0.1

Type RM Length L Ch R = 1 ,760.5   ,378.6,355.7,331.7
XS GIS Cut Line= 3
     1823976.724      434533.165     1823991.307      434490.109
     1824154.501      434299.831
#Sta/Elev= 28
       0  666.14     9.1  659.08    18.2  651.48    27.3  643.99    36.4  635.32
    45.5  624.71    55.1     615    59.1   613.3    64.7  610.91    74.1  610.62
    74.4  610.61   77.59  610.77      84  611.32    93.7  612.65   103.3  613.53
     113  613.79   122.6  613.84   132.2  613.72   151.5  613.33   190.1  612.81
   199.7  613.02   209.4  613.98     219  615.29   228.6  615.78   238.3     616
   257.6  616.11   276.8  616.35   296.1  616.16
#Mann= 3 , 0 , 0
       0     .06       0    59.1    .045       0    74.1     .06       0
#XS Ineff= 2 , 0
                          138.84          616.73
Permanent Ineff=
       F       F
Bank Sta=59.1,74.1
XS Rating Curve= 0 ,0
Exp/Cntr=0.3,0.1

Type RM Length L Ch R = 1 ,404.8   ,207.3,226.2,244.7
XS GIS Cut Line= 3
     1824361.967      434502.002     1824312.488      434362.679
     1824236.967      434306.689
#Sta/Elev= 29
       0  620.76     9.2  619.13    18.5  615.15    27.7  609.12    32.9  606.88
      37  605.11    46.2  604.57    47.9  604.64    55.4  604.96    64.7   606.1
    73.9  606.82    83.2   607.1    92.4   607.4   101.6  608.05   110.9  608.99
   120.1  609.88   129.4  610.56   138.6  611.25   147.8  611.85   157.2  612.49
   166.6  613.04     176  613.52   185.4  614.11   194.8   614.3   204.3  614.31
   213.7  614.28   223.1  614.24   232.5  614.32   241.9  614.63
#Mann= 3 , 0 , 0
       0     .06       0      37    .045       0    55.4     .06       0
Bank Sta=37,55.4
XS Rating Curve= 0 ,0
Exp/Cntr=0.3,0.1

Type RM Length L Ch R = 1 ,178.6   ,172.9,178.6,183.8
XS GIS Cut Line= 4
     1824509.102      434584.033     1824529.935      434500.699
     1824614.571      434340.543     1824588.529      434151.741
#Sta/Elev= 30
       0   614.7     9.5  615.44    19.1  616.33    57.3  618.61    66.8   618.9
    76.4  618.32    85.9  616.52    95.4  612.81     105  607.72   114.5  603.19
     124  601.48     125  601.47   133.6   601.4   143.1   601.4   152.6  601.88
   162.2  602.11   181.2   602.1   200.3  603.12   209.8  603.16   228.9  603.42
     248  603.92     267  604.01   314.7  604.88   324.2  604.96   333.8  605.01
   371.9   604.8     410  604.86   419.5  605.04   448.1  605.95   457.6  606.06
#Mann= 3 , 0 , 0
       0     .06       0     125    .045       0   143.1     .06       0
#XS Ineff= 2 , 0
       0                     204       0     606
Permanent Ineff=
       F       F
Bank Sta=125,143.1
XS Rating Curve= 0 ,0
Exp/Cntr=0.3,0.1

Chan Stop Cuts=-1
Use User Specified Reach Order=0
Composite Channel Slope=5